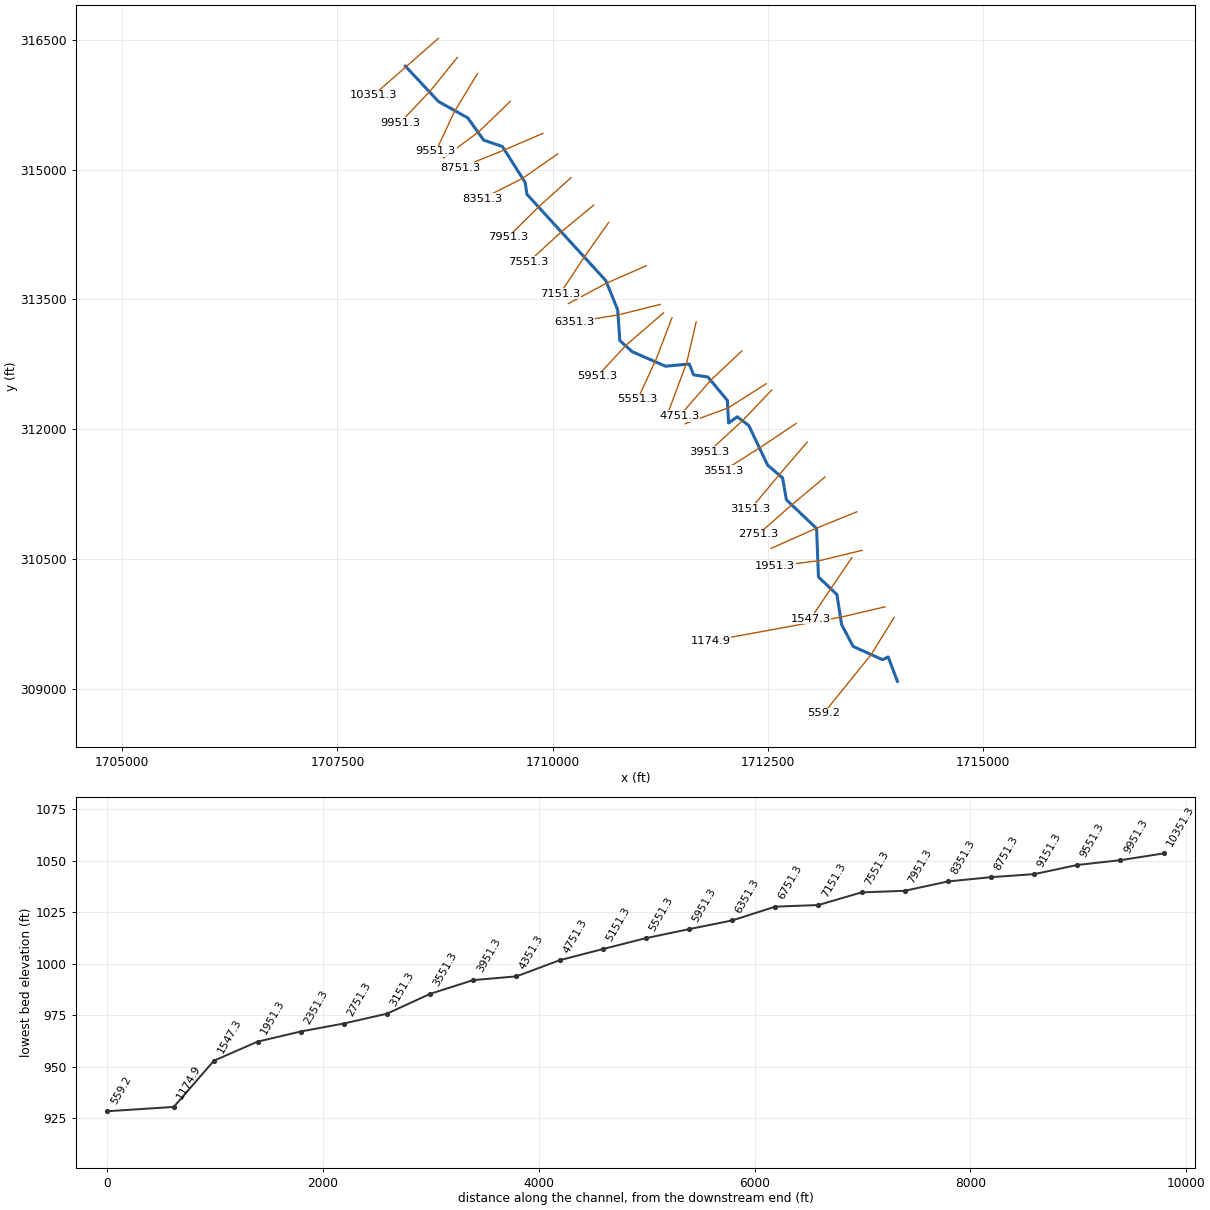
--- IsaacCrk.prj (project) ---

Proj Title=IsaacCrk
Current Plan=p01
Default Exp/Contr=0,0
English Units
Geom File=g01
Flow File=f01
Plan File=p01
BEGIN DESCRIPTION:
END DESCRIPTION:
DSS Export Rating Curves= 0
DSS Export Rating Curve Sorted= 0
DSS Export Volume Flow Curves= 0
DXF OffsetX= 0
DXF OffsetY= 0
DXF ScaleX= 0
DXF ScaleY= 0

--- IsaacCrk.p01 (plan) ---

Plan Title=Floodplain
Program Version=4.00
Geom File=g01
Flow File=f01
K Sum by GR=0
Std Step Tol=0.01
Critical Tol=0.01
Num of Std Step Trials=20
Max Error Tol=0.3
Flow Tol Ratio=0.001
Split Flow NTrial=30
Split Flow Tol=0.02
Split Flow Ratio=0.02
Log Output Level=0
Friction Slope Method=1
Unsteady Friction Slope Method=2
Unsteady Bridges Friction Slope Method=1
Global Log Level=0
CheckData=False
Run HTab=0
Run UNet=0
Run PostProcess=0
UNET Theta=0
UNET Theta Warmup=0
UNET ZTol=0
UNET ZSATol=0
UNET MxIter=0
UNET MaxInSteps=0
UNET DtIC=0
UNET DtMin=0
UNET MaxCRTS=0
UNET WFStab=0
UNET SFStab=0
UNET WFX=0
UNET SFX=0
UNET DSS MLevel=0
UNET DZMax Abort=0
UNET Convert EG Bridges=0
UNET Use Existing IB Tables=0
UNET Froude Limit=0
UNET Froude Power=0
Write IC File=0
Echo Input=False
Echo Output=False
Write Detailed=0

--- IsaacCrk.f01 (steady flow) ---

Flow Title=NFF Regression Equation
Program Version=4.00
Number of Profiles= 1
Profile Names=P100yr
River Rch & RM=IsaacCrk,Main            ,10351.3
     722
River Rch & RM=IsaacCrk,Main            ,8351.3
780.4385
River Rch & RM=IsaacCrk,Main            ,6351.3
859.0876
River Rch & RM=IsaacCrk,Main            ,5951.3
986.0567
River Rch & RM=IsaacCrk,Main            ,4751.3
1040.488
Boundary for River Rch & Prof#=IsaacCrk,Main            , 1
Up Type= 0
Dn Type= 3
Dn Slope=0.0188
DSS Import GetInterval= 0
DSS Import GetPeak= 0
DSS Import FillOption= 0

--- IsaacCrk.g01 (geometry) ---

Geom Title=USGS 3m DEM
Program Version=4.00

River Reach=IsaacCrk        ,Main
Reach XY= 30
     1708289.096      316197.814     1708673.881      315788.566
      1709013.78      315599.331     1709197.774      315342.357
     1709416.039      315268.573     1709679.465      314853.546
     1709701.102      314715.649     1710617.032      313717.242
      1710754.41      313380.071     1710779.779      313023.579
     1710923.895       312894.78     1711311.313      312727.253
     1711585.715      312753.298     1711635.419      312628.018
      1711802.93      312602.425     1712028.464      312332.256
     1712042.765      312070.204     1712143.157      312142.724
     1712277.919      312040.519     1712496.169      311583.355
     1712669.742      311435.589     1712713.972      311183.064
     1713064.584        310850.6     1713086.634      310289.814
     1713300.384      310087.046     1713355.158      309739.892
     1713488.833      309486.714     1713831.151      309333.099
     1713895.938      309365.224     1714003.976      309082.462

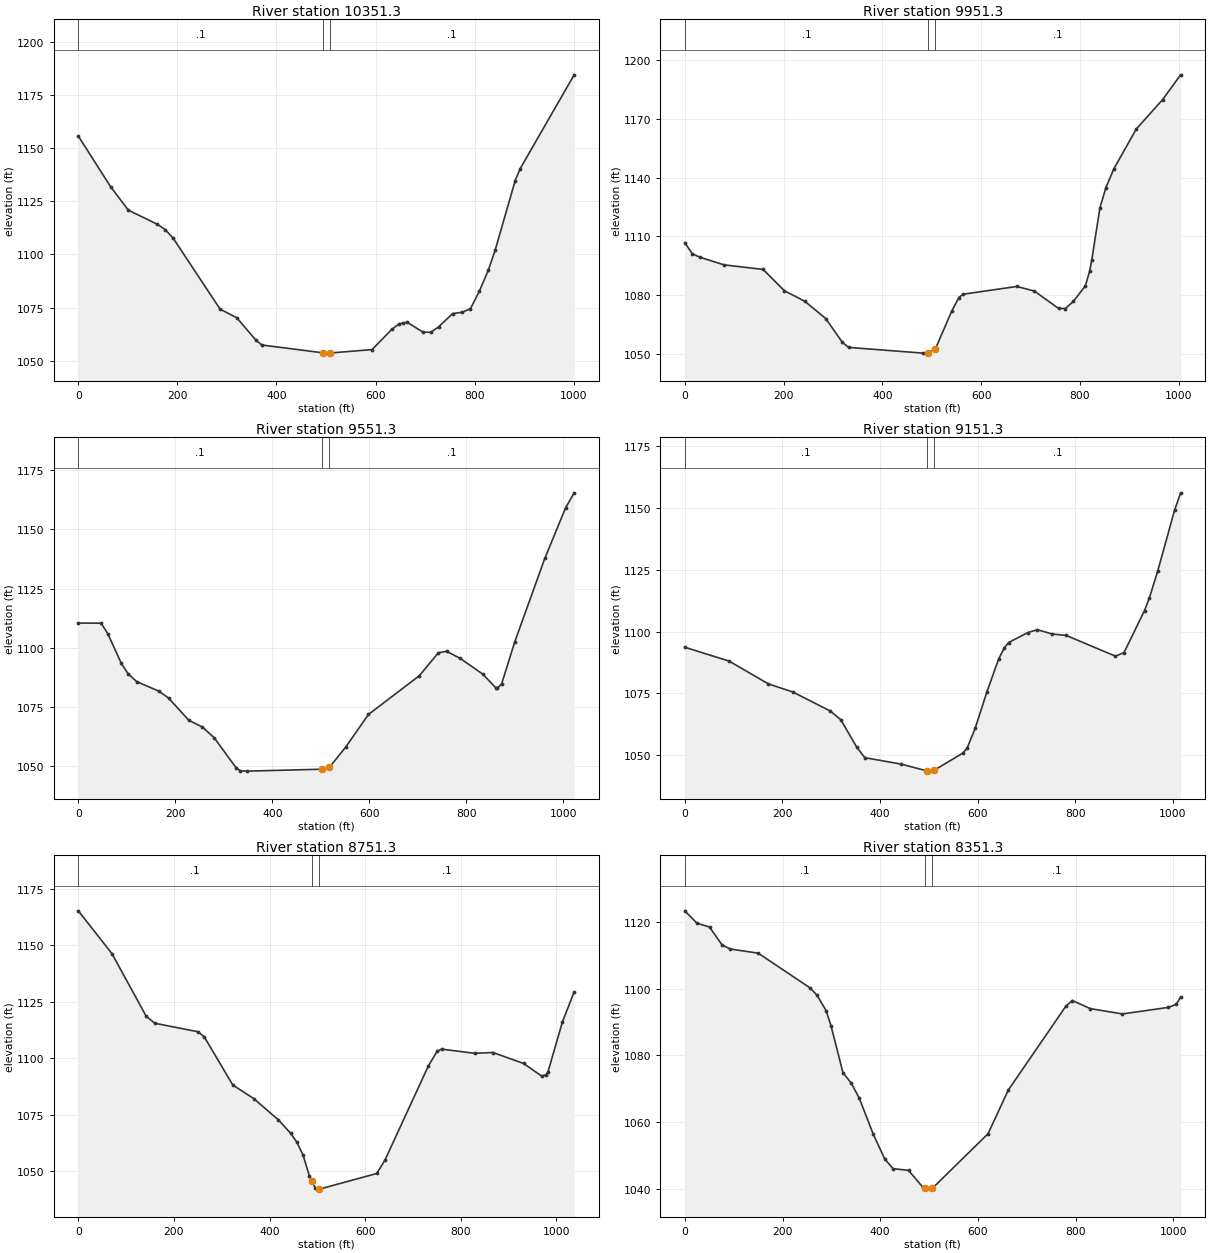
Type RM Length L Ch R = 1 ,10351.3 ,396.106,400,402.088
XS GIS Cut Line= 3
     1708672.693      316519.457     1708295.673      316190.281
     1707918.654      315861.105
#Sta/Elev= 30
       0 1155.58    65.2  1131.8   100.9 1120.81   159.8 1114.14   175.6  1111.6
   191.3 1107.69   286.2 1074.32   319.7 1070.29   358.4 1059.78   370.2 1057.48
     493 1053.82   504.8 1053.65     508 1053.71   593.1 1055.31   632.6 1064.77
   647.3  1067.3   656.3 1067.87   664.2 1068.11   695.7 1063.52   711.4 1063.44
   727.2 1065.95   755.6 1072.23   774.5 1072.84   791.7 1074.51   809.7 1082.79
   827.8 1092.68   841.4 1101.91   881.9 1134.65   891.9 1140.25    1001 1184.36
#Mann= 3 , 0 , 0
       0      .1       0     493    .045       0     508      .1       0
Bank Sta=493,508
XS Rating Curve= 0 ,0
Exp/Cntr=0.3,0.1

Type RM Length L Ch R = 1 ,9951.3  ,394.764,400,408.181
XS GIS Cut Line= 3
     1708891.871      316297.972     1708577.015      315909.712
     1708229.247        315544.9
#Sta/Elev= 30
       0 1106.74    15.2  1101.1    30.2 1099.34    79.5 1095.43   158.7 1093.08
   201.8 1082.18   243.1 1076.82   285.3 1068.03   319.1 1055.84   331.8 1053.28
   482.5 1050.36   492.4 1050.39   507.4 1052.55   540.9 1072.07   555.1 1078.74
   563.5 1080.44   672.1  1084.4   707.7 1082.05   756.7  1073.2   770.5 1073.11
   786.9 1076.81     811 1084.71   819.7 1092.19   823.9 1097.82   840.6 1124.65
   852.5 1134.75   868.9 1144.55   914.2  1164.8   967.3 1179.75  1003.9 1192.44
#Mann= 3 , 0 , 0
       0      .1       0   492.4    .045       0   507.4      .1       0
Bank Sta=492.4,507.4
XS Rating Curve= 0 ,0
Exp/Cntr=0.3,0.1

Type RM Length L Ch R = 1 ,9551.3  ,405.941,400,388.522
XS GIS Cut Line= 3
     1709125.522      316110.141     1708860.042      315674.845
     1708642.421       315211.17
#Sta/Elev= 30
       0 1110.51      47 1110.45    60.9 1105.96    88.7 1093.45   102.6 1089.11
   120.4 1085.78     166 1081.78   186.1 1078.85   227.8 1069.48   255.6 1066.65
     280 1062.14   325.1 1049.46     334 1048.17   348.4 1048.03   502.4 1048.84
   517.4 1049.59   551.2 1058.18     598 1071.93   702.9 1088.28   742.2 1097.98
   759.1  1098.6     787 1095.61     834 1088.93   860.3 1083.22   863.7 1082.91
   872.6 1084.85   899.6 1102.55   961.8 1137.91  1004.5 1159.13  1022.1 1165.45
#Mann= 3 , 0 , 0
       0      .1       0   502.4    .045       0   517.4      .1       0
Bank Sta=502.4,517.4
XS Rating Curve= 0 ,0
Exp/Cntr=0.3,0.1

Type RM Length L Ch R = 1 ,9151.3  ,409.314,400,392.483
XS GIS Cut Line= 3
      1709507.09      315789.673     1709143.706        315441.1
     1708732.298      315135.425
#Sta/Elev= 30
       0 1093.69    90.7  1088.1   171.4 1078.85   220.8 1075.64   298.2 1067.89
   319.5  1064.4   352.4 1053.27   368.8 1049.02   443.4 1046.41     496 1043.67
   502.2 1043.57     511 1043.92   570.1  1050.9   578.6 1052.86   595.5 1061.13
   619.1 1075.64   643.5 1089.09   654.9 1093.44   663.4 1095.57   703.2 1099.64
   722.6 1100.81   752.2 1099.07   781.8 1098.46   882.4  1090.1   900.1 1091.52
   942.1 1108.54   951.9 1113.54   968.9 1124.35  1003.6 1149.06  1016.1 1156.17
#Mann= 3 , 0 , 0
       0      .1       0     496    .045       0     511      .1       0
Bank Sta=496,511
XS Rating Curve= 0 ,0
Exp/Cntr=0.3,0.1

Type RM Length L Ch R = 1 ,8751.3  ,395.307,400,401.968
XS GIS Cut Line= 3
     1709887.012      315420.515     1709430.921      315225.661
     1708929.023      315023.751
#Sta/Elev= 30
       0  1165.3    70.4 1146.33   142.1 1118.58     160 1115.54   250.7 1111.75
   263.6 1109.44   323.1 1088.19   366.9 1082.18   418.5 1072.74   444.4 1066.75
   457.3 1062.81   470.2 1057.06   483.1 1048.04   488.5 1045.51     496  1042.4
   503.5 1042.12   504.1  1042.1     624 1049.02   640.9 1054.78   732.2 1096.69
   750.5 1103.15   759.6 1104.08   828.7 1102.23   867.1 1102.57   931.1 1097.75
   969.4  1092.1   978.6 1092.82   982.3 1094.06  1012.4  1116.1    1037 1129.39
#Mann= 3 , 0 , 0
       0      .1       0   488.5    .045       0   503.5      .1       0
Bank Sta=488.5,503.5
XS Rating Curve= 0 ,0
Exp/Cntr=0.3,0.1

Type RM Length L Ch R = 1 ,8351.3  ,397.144,400,407.126
XS GIS Cut Line= 3
     1710056.974      315181.872     1709646.199      314897.982
     1709185.517      314666.589
#Sta/Elev= 30
       0 1123.25      25 1119.53    50.6 1118.41    76.2 1113.06    93.3 1111.82
   150.2 1110.59   255.9 1100.25   270.4 1098.08   289.5 1093.32   299.2  1088.9
   323.7 1074.88   340.8 1071.69     357 1067.25   385.8 1056.43     409 1049.09
   426.1 1046.14     458 1045.62   486.8 1040.65   491.8 1040.48   501.1 1040.01
   506.8 1040.27   620.7 1056.58   662.2 1069.65   780.1 1094.74   793.4 1096.41
   830.3 1093.99   895.8 1092.41   989.4 1094.36    1006 1095.28  1014.9 1097.45
#Mann= 3 , 0 , 0
       0      .1       0   491.8    .045       0   506.8      .1       0
Bank Sta=491.8,506.8
XS Rating Curve= 0 ,0
Exp/Cntr=0.3,0.1

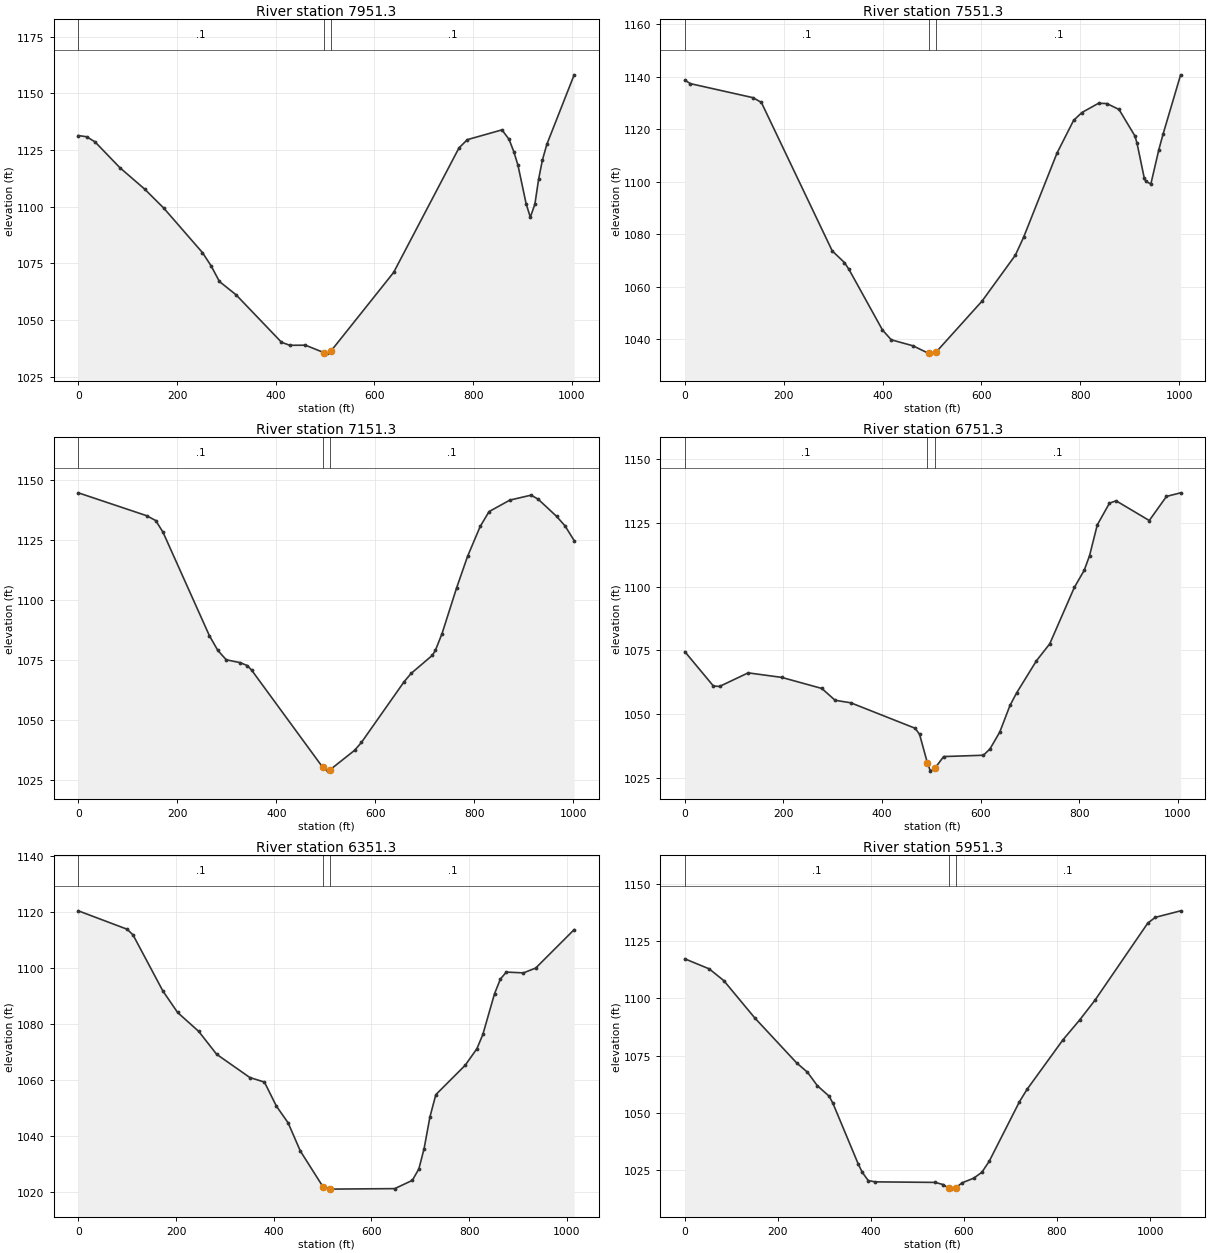
Type RM Length L Ch R = 1 ,7951.3  ,400.917,400,399.173
XS GIS Cut Line= 3
      1710212.83      314908.241     1709836.881      314571.107
     1709481.045      314220.262
#Sta/Elev= 30
       0  1131.4    16.9 1130.87    33.7 1128.64    84.1 1117.25   134.6 1107.76
   173.2 1099.39   251.6 1079.78   268.9 1074.01   285.9 1067.06   319.6  1061.2
   411.6 1040.29   428.4 1038.94   460.2 1038.98   497.5 1035.72   504.5 1035.48
   512.5 1036.56   638.9 1071.06   771.3 1125.94   788.2 1129.59   858.4  1133.9
   872.8 1129.73   882.3 1124.34   890.7 1118.43   907.5 1101.22   915.9  1095.4
   925.1 1101.12   932.7 1112.17   940.4 1120.65   949.5 1127.62  1004.7 1158.17
#Mann= 3 , 0 , 0
       0      .1       0   497.5    .045       0   512.5      .1       0
Bank Sta=497.5,512.5
XS Rating Curve= 0 ,0
Exp/Cntr=0.3,0.1

Type RM Length L Ch R = 1 ,7551.3  ,394.013,400,405.481
XS GIS Cut Line= 3
     1710475.221      314590.606     1710089.429      314271.963
     1709718.972      313932.739
#Sta/Elev= 30
       0 1138.67    11.4 1137.33   137.9 1131.99   154.8  1130.2   298.2 1073.62
   322.8 1069.21   331.9 1066.62   399.8  1043.5   417.5 1039.78   461.4 1037.49
   492.1  1034.7   492.9 1034.72   507.9 1035.03   601.4 1054.58   668.4 1071.98
     685 1078.75   752.7 1110.88   786.3 1123.35   803.1 1126.34   836.7 1129.86
   853.5 1129.75   878.1  1127.5   910.3  1117.4   914.5 1114.67   929.1 1101.43
   932.1 1100.14   942.5 1099.11   958.6 1112.15   967.2 1118.11  1002.7 1140.69
#Mann= 3 , 0 , 0
       0      .1       0   492.9    .045       0   507.9      .1       0
Bank Sta=492.9,507.9
XS Rating Curve= 0 ,0
Exp/Cntr=0.3,0.1

Type RM Length L Ch R = 1 ,7151.3  ,412.325,400,388.812
XS GIS Cut Line= 3
     1710648.905      314389.849     1710359.998      313980.585
     1710083.278      313563.573
#Sta/Elev= 30
       0 1144.55   137.8 1135.03   156.3    1133     171 1128.14   264.7 1085.02
   281.8 1078.84   298.8 1074.96   326.8 1073.78   341.4 1072.53   349.9 1070.68
   493.5 1030.18   503.3 1028.56   508.5 1029.15   558.2 1037.27   571.8 1040.53
   657.9 1065.81   672.1 1069.28   714.9  1076.8   721.2 1078.92   734.5 1085.85
   764.1    1105   786.1 1118.06   811.6 1130.54   829.5 1136.72   871.5 1141.52
   914.4 1143.58   928.6 1141.92   965.8 1134.77   982.9  1130.8  1001.4 1124.66
#Mann= 3 , 0 , 0
       0      .1       0   493.5    .045       0   508.5      .1       0
Bank Sta=493.5,508.5
XS Rating Curve= 0 ,0
Exp/Cntr=0.3,0.1

Type RM Length L Ch R = 1 ,6751.3  ,403.207,400,392.616
XS GIS Cut Line= 3
     1711086.867      313889.303     1710628.948       313689.88
     1710182.126      313451.567
#Sta/Elev= 30
       0 1074.54      58 1061.09    70.4 1060.91   128.6 1066.23   196.7 1064.45
   278.1 1060.12   304.9  1055.5   336.8 1054.51   467.3 1044.55   476.3 1042.16
     492 1031.11   498.3 1027.77     507 1028.81   525.1 1033.47   605.9 1033.99
   619.3 1036.51   638.9 1043.02   659.7 1053.47   673.2  1058.4   713.5 1070.99
   740.4  1077.6   790.3 1099.68   810.4  1106.4   821.2 1112.14   836.8 1124.13
   861.5 1132.64     875 1133.57   942.3 1125.85   977.2 1135.29  1005.9 1136.69
#Mann= 3 , 0 , 0
       0      .1       0     492    .045       0     507      .1       0
Bank Sta=492,507
XS Rating Curve= 0 ,0
Exp/Cntr=0.3,0.1

Type RM Length L Ch R = 1 ,6351.3  ,389.047,400,415.46
XS GIS Cut Line= 3
     1711249.162      313441.905     1710755.631      313319.921
     1710255.439      313240.933
#Sta/Elev= 30
       0 1120.55    99.6 1113.99   111.9 1111.96     173 1091.91   203.2 1084.21
   246.4 1077.45   283.1 1069.27     351 1060.96   380.9 1059.32   405.4 1050.73
   429.4 1044.75   454.3 1034.71   500.9 1021.85   515.3 1021.06   515.9 1021.07
   647.6 1021.24   683.6  1024.2     697 1028.31   707.7 1035.57   719.7 1046.92
   731.7 1054.84   791.8 1065.34   815.8 1071.27   827.9 1076.35   851.9 1090.96
   863.9 1096.18   875.9 1098.65   911.1 1098.37     936 1100.08  1014.8 1113.83
#Mann= 3 , 0 , 0
       0      .1       0   500.9    .045       0   515.9      .1       0
Bank Sta=500.9,515.9
XS Rating Curve= 0 ,0
Exp/Cntr=0.3,0.1

Type RM Length L Ch R = 1 ,5951.3  ,388.787,400,407.042
XS GIS Cut Line= 3
     1711287.195      313345.109     1710851.541      312970.104
     1710517.217      312610.754
#Sta/Elev= 30
       0 1117.21    52.5 1112.82    83.8 1107.71   150.2 1091.49   240.5 1071.82
   263.7 1067.78   284.9 1061.91   310.2 1057.34   318.3 1054.26   372.9 1027.72
   381.5 1024.12   394.3 1020.56   409.3 1020.01   538.1 1019.77   554.9 1018.84
   567.3 1017.28   571.1 1016.84   582.3 1017.48   596.3 1019.61   621.1 1021.63
   638.6 1024.22   654.3 1029.02   719.2 1054.93   735.4 1060.28   812.9 1081.96
   848.4  1090.5   881.4 1099.14   994.9 1132.74  1011.1 1135.28  1065.6 1138.12
#Mann= 3 , 0 , 0
       0      .1       0   567.3    .045       0   582.3      .1       0
Bank Sta=567.3,582.3
XS Rating Curve= 0 ,0
Exp/Cntr=0.3,0.1

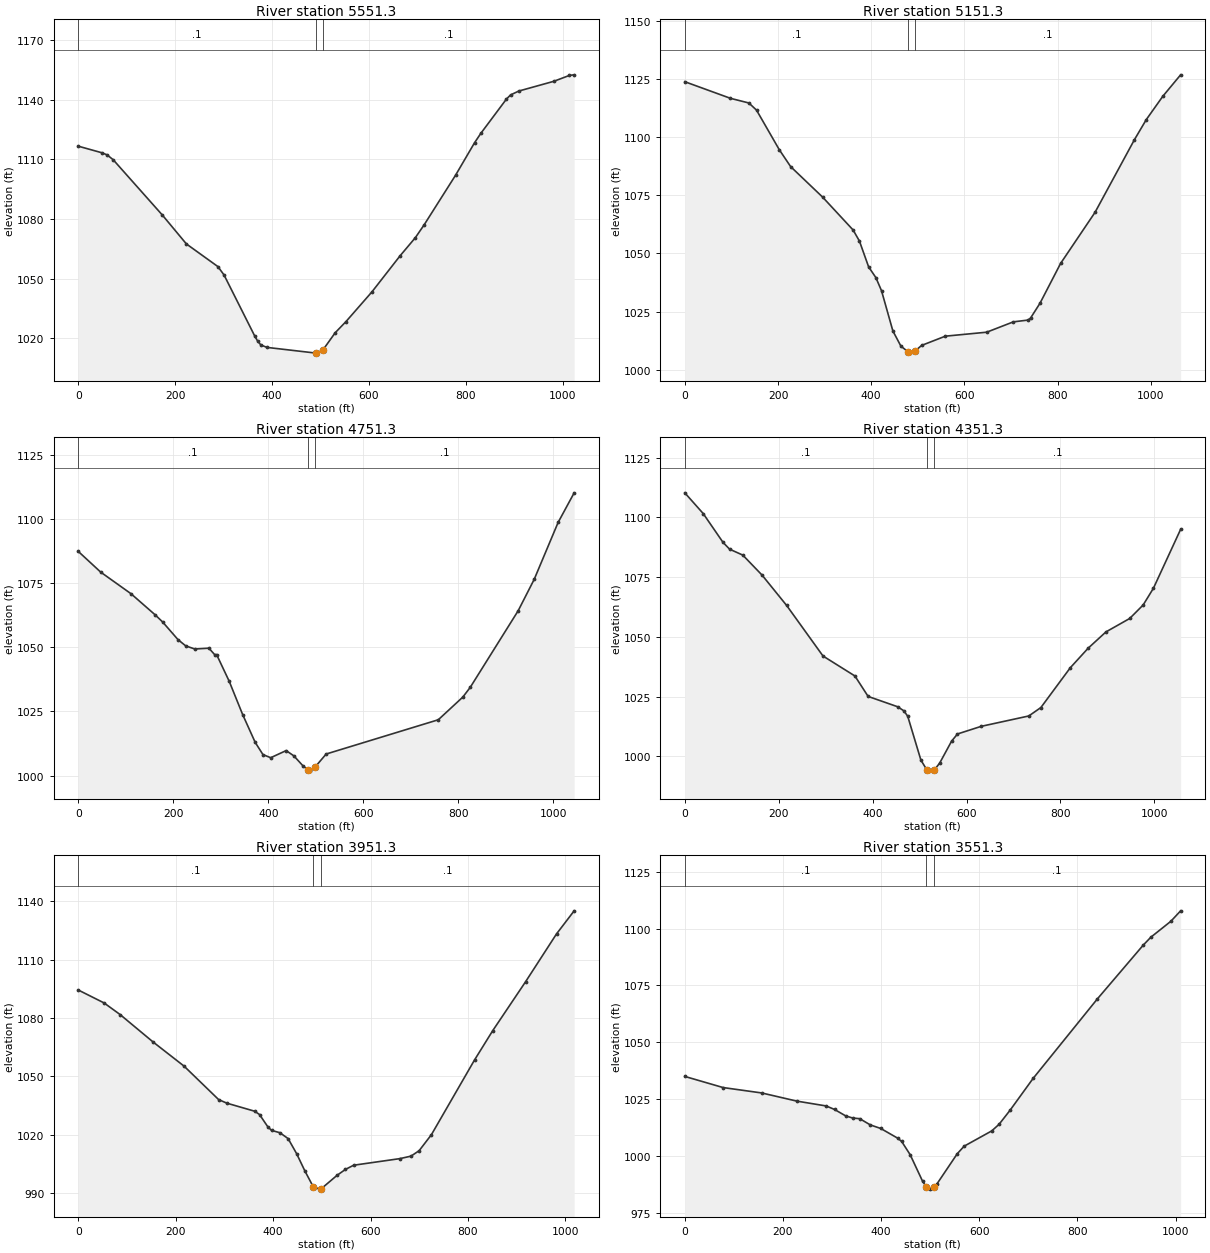
Type RM Length L Ch R = 1 ,5551.3  ,396.932,400,401.736
XS GIS Cut Line= 3
     1711385.088      313287.909     1711207.372      312822.977
     1710987.076      312345.068
#Sta/Elev= 30
       0  1116.7    48.4 1113.41    59.4 1112.33    72.1 1109.85   173.8 1081.93
   223.2 1067.45   288.2 1056.05   300.9 1051.83   364.4 1021.01   370.3 1018.51
   377.1 1016.52   389.8 1015.32   490.2 1012.47   491.5 1012.44   505.2 1014.06
   530.6 1022.75   552.7 1028.32   606.4 1043.31   664.7 1061.54   695.9 1070.57
   714.1 1077.05     779 1102.05   818.2  1118.4   831.3 1123.19   884.2 1140.46
   892.7 1142.54   909.7 1144.49   982.2 1149.41  1014.3 1152.37    1024 1152.66
#Mann= 3 , 0 , 0
       0      .1       0   490.2    .045       0   505.2      .1       0
Bank Sta=490.2,505.2
XS Rating Curve= 0 ,0
Exp/Cntr=0.3,0.1

Type RM Length L Ch R = 1 ,5151.3  ,412.874,400,392.115
XS GIS Cut Line= 3
     1711666.267      313239.892     1711555.725      312765.803
      1711352.77      312225.543
#Sta/Elev= 30
       0 1123.87    97.9 1116.73   137.5 1114.72   153.9 1111.65   202.7 1094.64
   227.1 1087.36   295.7 1074.24   361.2 1060.08   374.7 1055.35   394.5  1044.2
     410 1039.62   422.1 1033.98   446.5 1016.67   463.7 1010.15   479.3 1007.67
   483.1 1007.14   494.3 1008.11   508.3 1010.47     559 1014.43   647.8 1016.14
     705 1020.59   736.6 1021.36   741.9 1022.22     762 1028.54   806.4 1045.73
   880.2 1067.67   964.9 1098.98   990.3  1107.6  1025.9 1117.66  1063.9 1126.83
#Mann= 3 , 0 , 0
       0      .1       0   479.3    .045       0   494.3      .1       0
Bank Sta=479.3,494.3
XS Rating Curve= 0 ,0
Exp/Cntr=0.3,0.1

Type RM Length L Ch R = 1 ,4751.3  ,403.935,400,388.716
XS GIS Cut Line= 3
     1712196.061      312903.393     1711837.633      312567.717
     1711472.562      312152.252
#Sta/Elev= 30
       0 1087.33    47.2 1079.26   110.8 1070.87   161.3  1062.7   177.3 1059.89
   209.9 1052.96   226.1 1050.53   245.2 1049.31   274.9 1049.63   287.2  1047.1
   291.2 1047.12   317.6 1036.78     346 1023.77   372.5  1012.9   388.8 1008.15
   405.1 1006.94   437.6 1009.71   453.9 1007.65   473.9 1003.59   483.6 1002.29
   488.8 1001.71   498.6 1003.32   521.9 1008.38     758 1021.73   809.7 1030.58
   825.3 1034.37   926.2 1064.22   959.9 1076.44  1010.3 1098.63  1044.1 1110.18
#Mann= 3 , 0 , 0
       0      .1       0   483.6    .045       0   498.6      .1       0
Bank Sta=483.6,498.6
XS Rating Curve= 0 ,0
Exp/Cntr=0.3,0.1

Type RM Length L Ch R = 1 ,4351.3  ,389.376,400,408.957
XS GIS Cut Line= 3
      1712479.67      312524.973     1712037.428      312245.219
     1711537.329      312062.009
#Sta/Elev= 30
       0  1110.3    39.2 1101.63    81.3  1089.6    95.4 1086.73   123.5 1084.25
   164.6 1075.87   216.9 1063.18   294.3 1042.04   362.3 1033.68   390.4 1025.13
   453.3 1020.81   466.4 1019.12   474.7 1016.86   502.8   998.5   515.8  994.29
   519.9  993.88   530.8   994.2   542.8  997.25   568.1  1006.4   580.7 1009.42
   631.3 1012.62   732.5 1016.95   758.3 1020.48     821 1037.14   858.9 1045.29
   896.8 1052.11   947.4 1057.73   976.1 1063.38     998 1070.39  1055.9 1095.02
#Mann= 3 , 0 , 0
       0      .1       0   515.8    .045       0   530.8      .1       0
Bank Sta=515.8,530.8
XS Rating Curve= 0 ,0
Exp/Cntr=0.3,0.1

Type RM Length L Ch R = 1 ,3951.3  ,404.504,400,395.873
XS GIS Cut Line= 3
     1712542.559      312451.392     1712203.674      312097.064
     1711814.286       311740.88
#Sta/Elev= 30
       0 1094.45    52.8 1087.83    85.7 1081.86   153.7  1067.7   217.1 1055.32
     288 1038.13   304.8 1036.29   362.2 1032.12     372 1030.43   388.8 1024.21
   396.6 1022.29   413.8 1021.08   430.7 1018.06   448.1 1010.35   465.3 1001.34
   482.8  993.05   496.8  992.07   497.8  992.07   531.2  999.17   548.4 1002.21
   565.2 1004.36     660 1007.75   682.9 1009.03   699.7 1011.83   724.9 1020.06
   813.4 1058.47   850.9  1073.6   918.2  1098.7   981.8 1123.33    1018 1135.19
#Mann= 3 , 0 , 0
       0      .1       0   482.8    .045       0   497.8      .1       0
Bank Sta=482.8,497.8
XS Rating Curve= 0 ,0
Exp/Cntr=0.3,0.1

Type RM Length L Ch R = 1 ,3551.3  ,393.811,400,407.038
XS GIS Cut Line= 3
     1712826.296      312064.711     1712410.259      311787.743
     1711978.566      311515.266
#Sta/Elev= 30
       0 1034.96    78.1 1030.06   156.7 1027.69     228 1024.11     288 1021.97
   305.1 1020.43   327.8  1017.6   342.1 1016.66   356.5 1016.37     378 1013.63
   399.3 1012.06   433.5 1007.83   441.9 1006.35   459.2 1000.53   484.7  988.76
   492.3  986.33     499  985.38   507.3  986.22     513  987.42   555.2 1000.96
   569.2 1004.27   625.4 1010.99   640.3 1013.88   662.6 1020.03   709.6 1034.05
   840.5 1069.02   934.2 1092.74   949.6  1096.2   990.4 1103.21  1010.3 1107.81
#Mann= 3 , 0 , 0
       0      .1       0   492.3    .045       0   507.3      .1       0
Bank Sta=492.3,507.3
XS Rating Curve= 0 ,0
Exp/Cntr=0.3,0.1

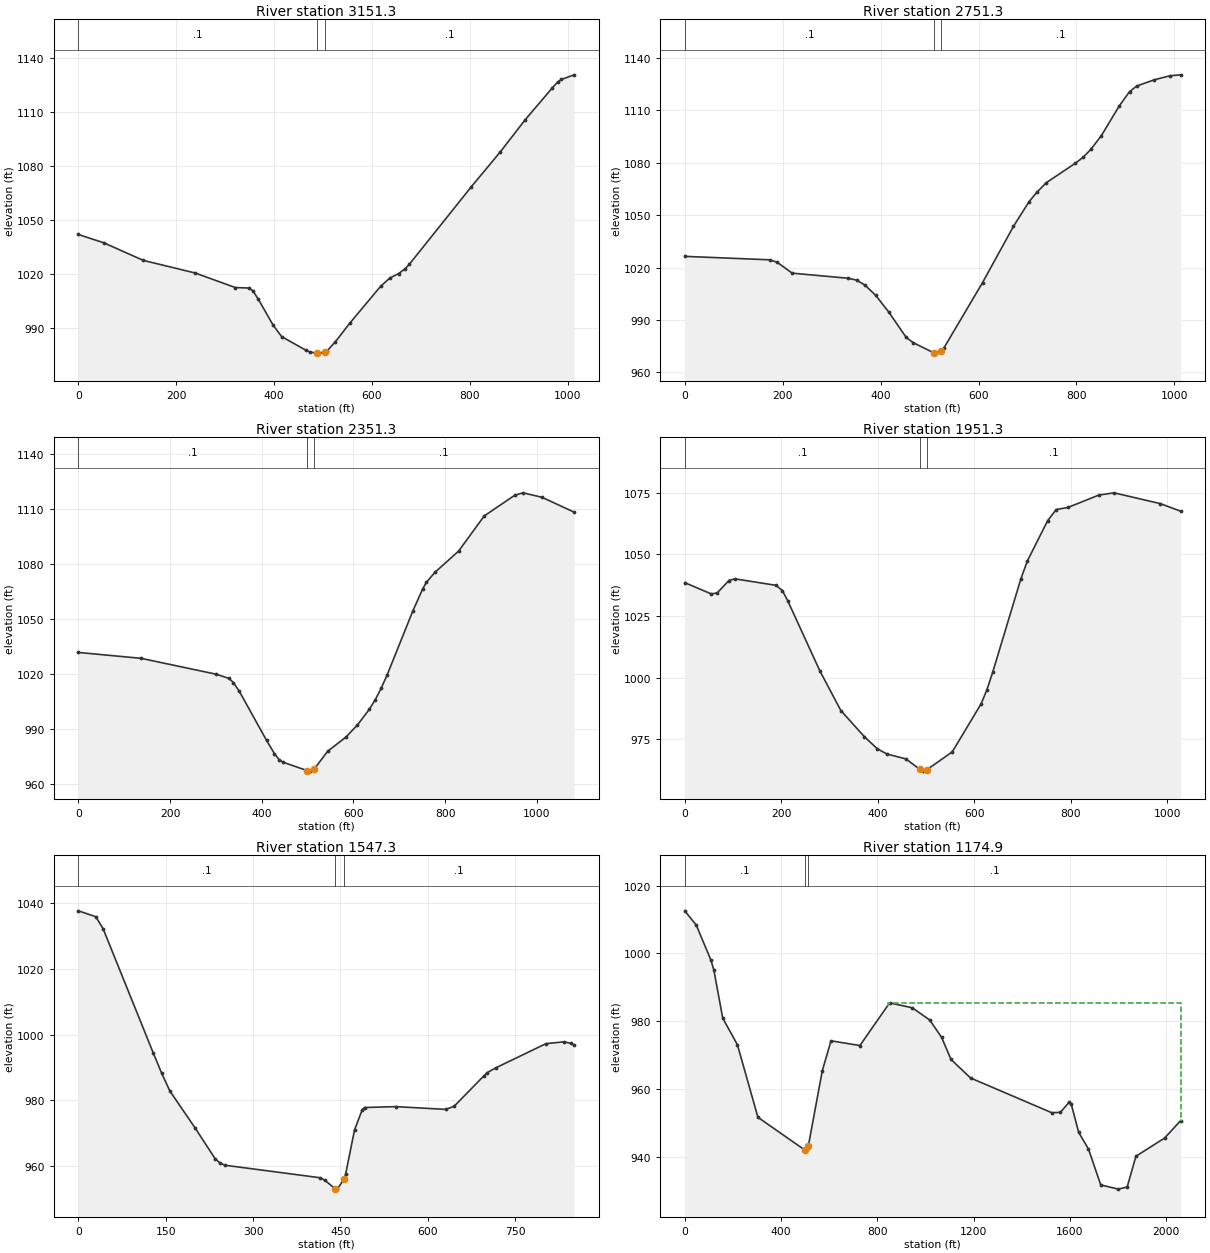
Type RM Length L Ch R = 1 ,3151.3  ,403.803,400,396.473
XS GIS Cut Line= 3
     1712955.118      311849.195     1712631.537      311473.187
     1712299.326      311076.811
#Sta/Elev= 30
       0 1041.79    51.6 1037.22     133 1027.35   238.5 1020.38     321 1012.24
   347.9    1012   356.4  1010.6     368 1005.68   398.4  991.17   415.6  984.92
   465.8  977.25   474.2   976.3   488.6  975.75   491.1  975.74   503.6  976.33
   507.9  976.83   525.3  982.06   555.3   992.6   617.7 1012.92   636.2 1017.49
   654.7 1020.05     668 1022.77   676.5 1025.22   803.1 1068.36   861.9 1087.64
   913.4 1105.73   968.9 1123.51   979.9 1126.74   987.4 1128.13  1013.3 1130.69
#Mann= 3 , 0 , 0
       0      .1       0   488.6    .045       0   503.6      .1       0
Bank Sta=488.6,503.6
XS Rating Curve= 0 ,0
Exp/Cntr=0.3,0.1

Type RM Length L Ch R = 1 ,2751.3  ,407.496,400,392.693
XS GIS Cut Line= 3
     1713161.158      311445.276      1712764.78      311114.422
     1712391.134      310786.042
#Sta/Elev= 30
       0  1026.4   173.1 1024.43   188.5 1023.05   219.4 1016.78   334.3 1013.84
   351.2 1012.75     368 1009.91   389.6 1004.17   416.4  994.59   452.3  979.93
   466.9  976.91   508.8  971.12   513.3  970.97   523.8  972.31     529  973.82
   608.1 1011.32   671.3 1043.57   702.9 1057.61   718.7 1062.98   738.5 1068.62
   797.7  1079.7   813.5 1083.13   829.3 1087.64   850.9 1095.53   886.9 1112.33
   908.4 1120.75   923.6 1124.03   958.8 1127.51   990.9 1129.83  1012.8 1130.38
#Mann= 3 , 0 , 0
       0      .1       0   508.8    .045       0   523.8      .1       0
Bank Sta=508.8,523.8
XS Rating Curve= 0 ,0
Exp/Cntr=0.3,0.1

Type RM Length L Ch R = 1 ,2351.3  ,402.952,400,393.856
XS GIS Cut Line= 3
     1713531.704      311043.504     1713061.769       310853.28
     1712536.319      310620.259
#Sta/Elev= 30
       0 1031.84   137.1 1028.62   301.2 1019.93   328.5 1017.67   338.1 1015.44
     351 1010.68   410.6   983.8   427.8  976.59   437.9  973.33   447.1  971.89
   499.5  967.33   504.7  967.08   514.5  968.23   543.6  977.89   583.4  985.63
   608.5  992.21   634.5 1000.78   647.5 1006.01   660.5 1012.34   673.5  1019.6
   729.8 1054.67   751.4 1066.73   759.1  1070.1   777.4 1075.49   829.3 1087.15
   885.2 1106.34   951.7 1117.61   969.7 1118.94  1011.1 1116.51  1081.3 1108.39
#Mann= 3 , 0 , 0
       0      .1       0   499.5    .045       0   514.5      .1       0
Bank Sta=499.5,514.5
XS Rating Curve= 0 ,0
Exp/Cntr=0.3,0.1

Type RM Length L Ch R = 1 ,1951.3  ,387.49,403.968,422.939
XS GIS Cut Line= 3
     1713592.004      310597.527     1713111.067      310481.529
     1712582.355      310413.036
#Sta/Elev= 30
       0 1038.48    54.7 1033.94    66.9 1034.28    91.3 1039.33   103.8 1040.03
     189  1037.4   202.2 1035.29   213.5 1031.07   280.2 1002.62   323.4  986.69
   372.2  976.07     399  971.19   418.7  969.09     458  967.09   487.2  962.85
   494.4  962.14   502.2  962.79   554.2  969.93   614.1  989.41   626.1  995.13
     638 1002.15   696.5 1040.06   709.9 1047.27     752 1063.62   769.7 1068.08
   794.3 1068.97   857.9 1073.95   889.5 1074.87   985.2 1070.51  1027.5 1067.44
#Mann= 3 , 0 , 0
       0      .1       0   487.2    .045       0   502.2      .1       0
Bank Sta=487.2,502.2
XS Rating Curve= 0 ,0
Exp/Cntr=0.3,0.1

Type RM Length L Ch R = 1 ,1547.3  ,389.999,372.414,354.028
XS GIS Cut Line= 3
     1713474.011      310513.093     1713221.133      310141.394
     1712996.108      309808.616
#Sta/Elev= 30
       0 1037.76    29.9 1035.97    42.5 1032.32   128.6  994.44     143  988.27
   157.3  982.77   200.4  971.57     235  962.13   243.5  960.81   252.1  960.17
   414.4  956.38     423  955.63     441     953   444.5  952.89     456  955.84
   457.2  956.23   458.9  957.47   474.3  970.98   487.5  977.14   491.4  977.78
   544.9  978.05   630.9  977.21   645.3  978.17   696.6  987.49   702.5  988.45
   716.9  989.89   802.8  997.25   833.4   997.8   845.8  997.37   851.3   996.8
#Mann= 3 , 0 , 0
       0      .1       0     441    .045       0     456      .1       0
Bank Sta=441,456
XS Rating Curve= 0 ,0
Exp/Cntr=0.3,0.1

Type RM Length L Ch R = 1 ,1174.9  ,597.617,615.687,631.688
XS GIS Cut Line= 3
     1713858.534      309944.356     1713373.271       309831.27
     1711836.368      309550.336
#Sta/Elev= 30
       0 1012.54    47.9 1008.29   108.8  997.96     121     995   157.6  980.88
   218.6  973.05   303.9  951.62   498.7  941.97   513.7  943.25   571.4  965.35
   607.6  974.19   727.6  972.79   851.2  985.38   945.5  983.93  1017.9  980.33
  1067.3   975.2  1106.3  968.69  1187.9  963.21  1524.8  952.98    1561  953.08
  1597.3  956.09  1606.3  955.45  1636.9  947.18  1677.7  942.25  1728.7  931.66
  1802.4  930.43  1838.6  931.07  1874.8  940.13    1994   945.5  2060.6  950.63
#Mann= 3 , 0 , 0
       0      .1       0   498.7    .045       0   513.7      .1       0
#XS Ineff= 2 , 0
                          843.32          985.32
Permanent Ineff=
       F       F
Bank Sta=498.7,513.7
XS Rating Curve= 0 ,0
Exp/Cntr=0.3,0.1

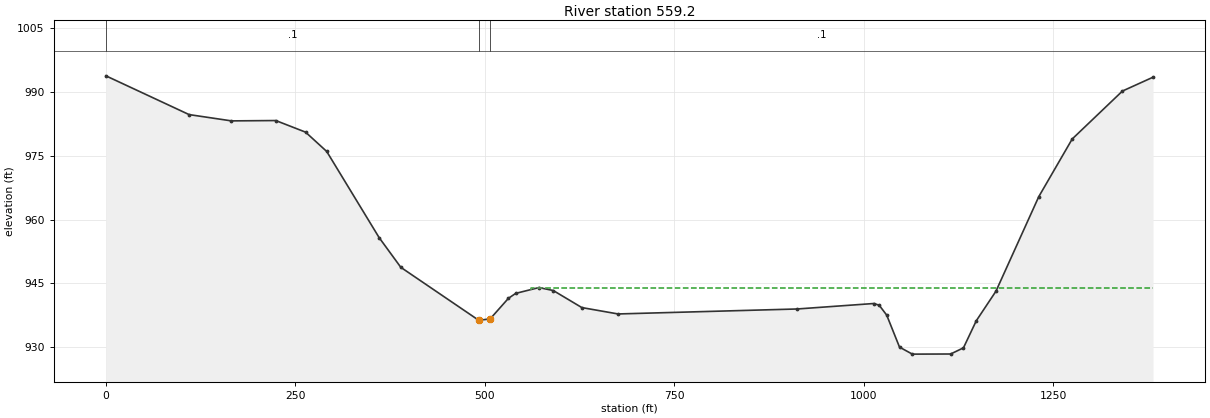
Type RM Length L Ch R = 1 ,559.2   ,577.43,559.231,541.101
XS GIS Cut Line= 3
     1713965.706      309823.322     1713699.558      309394.312
     1713146.419      308712.472
#Sta/Elev= 30
       0   993.8   109.8  984.68   165.7   983.2   224.2  983.28   263.5  980.55
   291.4  976.01   360.5  955.76   389.2  948.75   492.2  936.27   507.2  936.64
   531.2  941.46   540.8  942.62   571.5  943.99   590.4  943.29   628.1  939.28
   675.9  937.78   912.2  938.95  1013.5  940.24  1020.5  939.83  1030.4  937.51
  1047.3  929.98  1064.2  928.33  1114.8  928.36  1131.7  929.81  1148.6  936.17
  1174.6  943.14  1231.1  965.38  1275.2  978.94  1341.5  990.22  1381.9  993.48
#Mann= 3 , 0 , 0
       0      .1       0   492.2    .045       0   507.2      .1       0
#XS Ineff= 2 , 0
                          560.96          943.97
Permanent Ineff=
       F       F
Bank Sta=492.2,507.2
XS Rating Curve= 0 ,0
Exp/Cntr=0.3,0.1

Chan Stop Cuts=-1
Use User Specified Reach Order=0